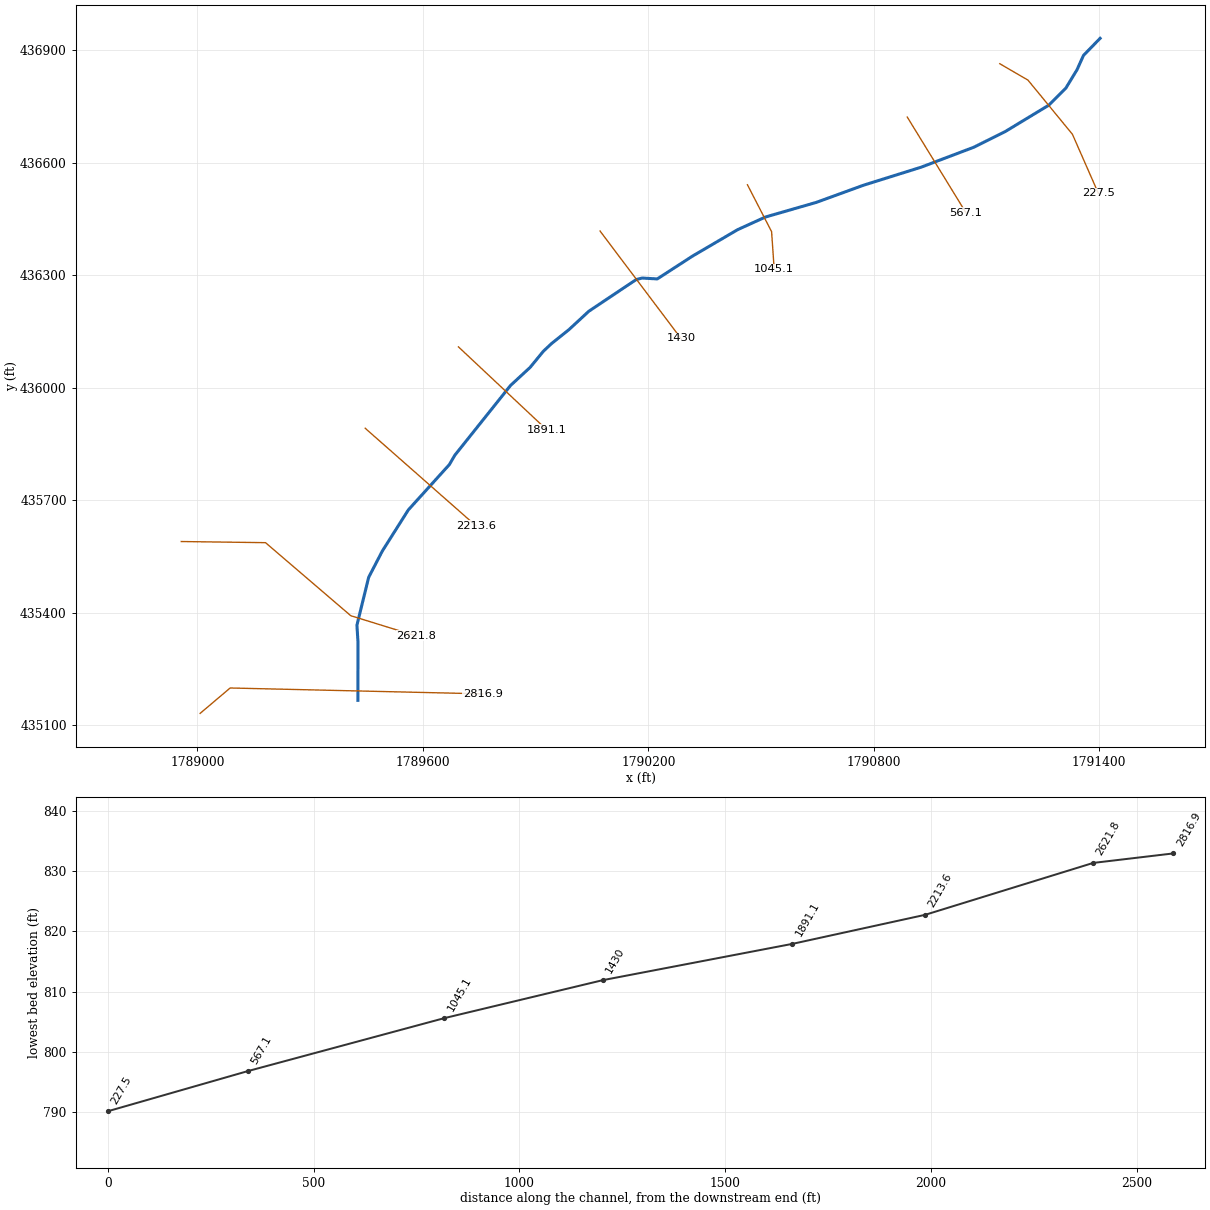
--- LENSCK.prj (project) ---

Proj Title=LENSCK
Current Plan=p01
Default Exp/Contr=0,0
English Units
Geom File=g01
Flow File=f01
Plan File=p01
BEGIN DESCRIPTION:
END DESCRIPTION:
DSS Export Rating Curves= 0
DSS Export Rating Curve Sorted= 0
DSS Export Volume Flow Curves= 0
DXF OffsetX= 0
DXF OffsetY= 0
DXF ScaleX= 0
DXF ScaleY= 0

--- LENSCK.p01 (plan) ---

Plan Title=Floodplain
Program Version=4.00
Geom File=g01
Flow File=f01
K Sum by GR=0
Std Step Tol=0.01
Critical Tol=0.01
Num of Std Step Trials=20
Max Error Tol=0.3
Flow Tol Ratio=0.001
Split Flow NTrial=30
Split Flow Tol=0.02
Split Flow Ratio=0.02
Log Output Level=0
Friction Slope Method=1
Unsteady Friction Slope Method=2
Unsteady Bridges Friction Slope Method=1
Global Log Level=0
CheckData=False
Run HTab=0
Run UNet=0
Run PostProcess=0
UNET Theta=0
UNET Theta Warmup=0
UNET ZTol=0
UNET ZSATol=0
UNET MxIter=0
UNET MaxInSteps=0
UNET DtIC=0
UNET DtMin=0
UNET MaxCRTS=0
UNET WFStab=0
UNET SFStab=0
UNET WFX=0
UNET SFX=0
UNET DSS MLevel=0
UNET DZMax Abort=0
UNET Convert EG Bridges=0
UNET Use Existing IB Tables=0
UNET Froude Limit=0
UNET Froude Power=0
Write IC File=0
Echo Input=False
Echo Output=False
Write Detailed=0

--- LENSCK.f01 (steady flow) ---

Flow Title=NFF Regression Equation
Program Version=4.10
Number of Profiles= 1
Profile Names=P100yr
River Rch & RM=LENSCK,Main            ,2816.9
 675.109
River Rch & RM=LENSCK,Main            ,2213.6
984.9176
River Rch & RM=LENSCK,Main            ,567.1
1072.954
Boundary for River Rch & Prof#=LENSCK,Main            , 1
Up Type= 0
Dn Type= 1
Dn Known WS=803.8
DSS Import GetInterval= 0
DSS Import GetPeak= 0
DSS Import FillOption= 0

--- LENSCK.g01 (geometry) ---

Geom Title=USGS 10m DEM
Program Version=4.10

River Reach=LENSCK          ,Main
Reach XY= 30
     1789426.983      435165.912     1789427.185      435321.513
     1789424.379      435366.433     1789455.629      435494.037
     1789492.087       435564.35     1789561.098      435673.725
     1789670.473      435794.819     1789684.796      435819.558
     1789833.233      436005.756     1789885.316      436053.933
     1789920.473      436096.902     1789942.608      436117.735
     1789988.181      436154.194     1790041.566      436203.673
     1790167.868      436288.308     1790183.493      436292.215
     1790223.671      436289.864     1790317.608      436350.808
       1790437.4      436421.121     1790511.618      436454.975
     1790647.035      436494.037     1790772.035       436539.61
     1790925.681      436587.787     1791066.306      436641.173
     1791149.639       436682.84     1791265.525      436753.152
     1791311.098      436798.725     1791341.046      436848.204
     1791357.973      436885.965     1791402.243      436931.537

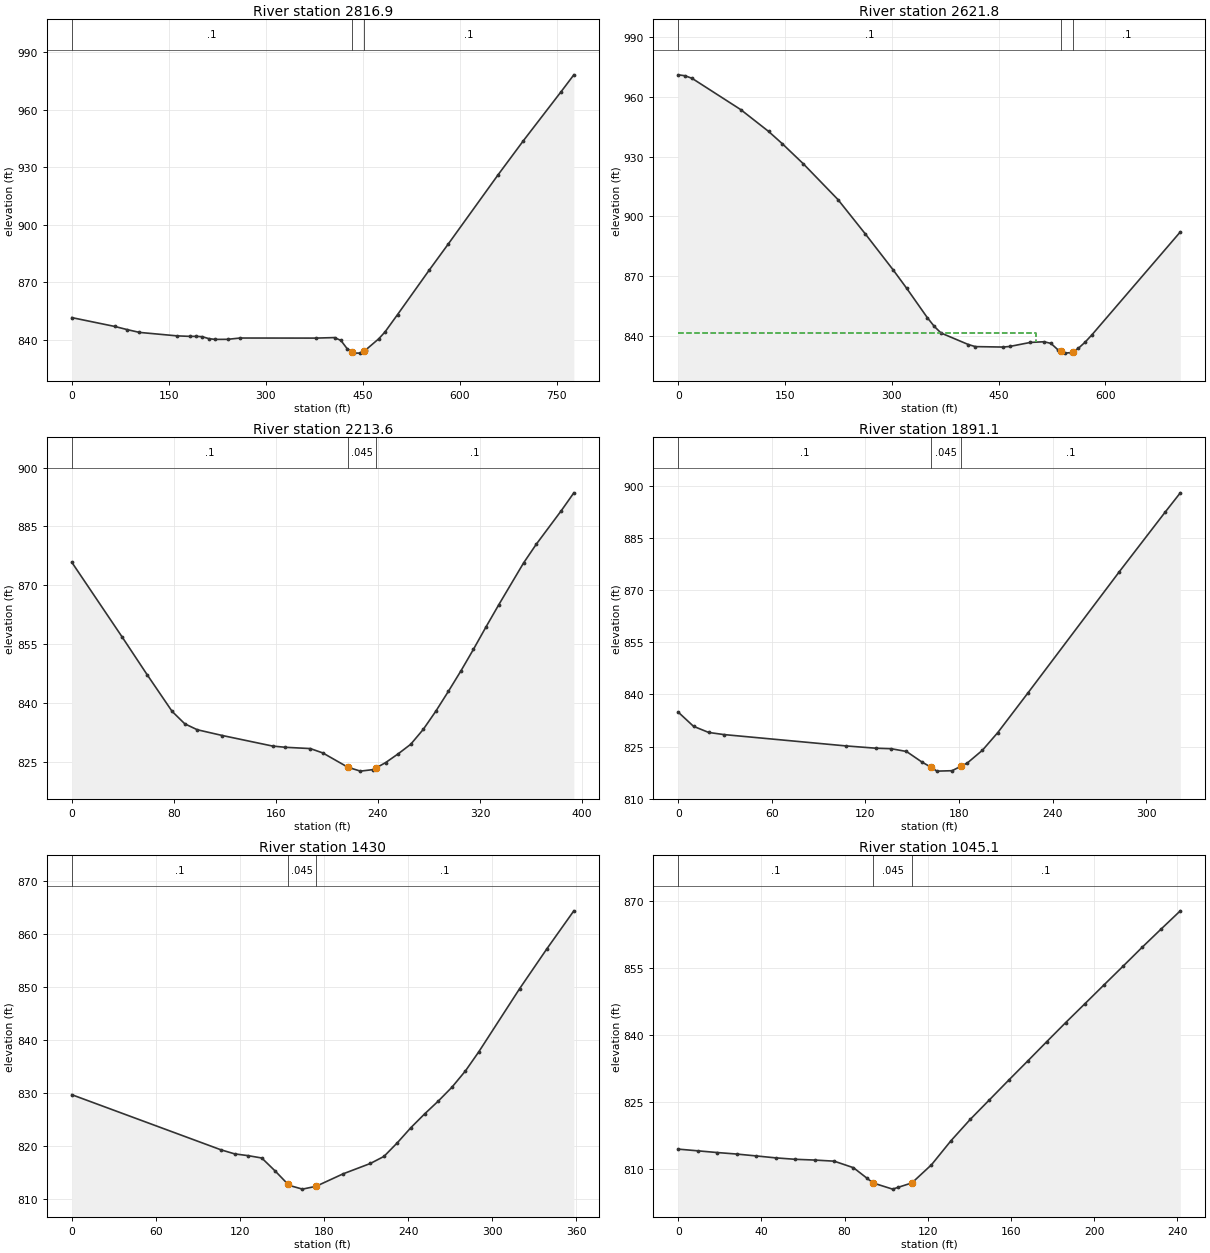
Type RM Length L Ch R = 1 ,2816.9  ,201.5,195.1,188.5
XS GIS Cut Line= 3
     1789007.133       435131.19     1789086.995      435198.899
      1789758.87      435183.274
#Sta/Elev= 30
       0  851.49    66.6  846.86    85.7  845.22   104.7  843.76   163.1  841.94
   182.6  841.69   192.4   841.7   202.1  841.51   211.8  840.52   221.6   840.1
   241.1  840.14   260.5  840.82   377.4  840.78   406.6  841.05   416.4  839.55
   426.1  835.24  433.29  833.62   435.9  832.98   445.6  832.93   452.1  834.16
   455.3  834.76   474.8  840.37   484.6  843.98     504  853.05   552.7  876.14
     582   889.7   659.9  926.23   698.8  943.93   757.3   969.6   776.8  978.31
#Mann= 3 , 0 , 0
       0      .1       0  433.29    .045       0   452.1      .1       0
Bank Sta=433.29,452.1
XS Rating Curve= 0 ,0
Exp/Cntr=0.3,0.1

Type RM Length L Ch R = 1 ,2621.8  ,417.3,408.2,398.5
XS GIS Cut Line= 4
     1788956.786      435589.524     1789181.104       435586.47
     1789408.175      435391.607     1789581.786      435337.787
#Sta/Elev= 30
       0  971.04     9.8  970.56    19.5  969.26    87.8  953.58   126.8  942.67
   146.3  936.42   175.6  926.42   224.3  908.46     263   891.1   301.6  873.28
   320.9   863.9   349.8  849.21   359.5  844.85   369.1  841.46   407.7  835.64
   417.4  834.62     456   834.4   465.6  834.69   494.6  836.72   513.9  837.06
   523.6  836.23   533.1  833.12     538  832.22   542.7  831.35   552.3  831.62
  554.48  832.05   561.8  833.68   571.4   836.8     581  840.48   705.3  892.19
#Mann= 3 , 0 , 0
       0      .1       0     538    .045       0  554.48      .1       0
#XS Ineff= 2 , 0
          502.41  841.25
Permanent Ineff=
       F       F
Bank Sta=538,554.48
XS Rating Curve= 0 ,0
Exp/Cntr=0.3,0.1

Type RM Length L Ch R = 1 ,2213.6  ,323,322.5,321.6
XS GIS Cut Line= 2
      1789446.37      435891.607     1789741.508       435631.19
#Sta/Elev= 29
       0   875.9    39.4  856.92      59  847.32    78.7  837.93    88.6  834.78
    98.4  833.27   118.1   831.8   157.4  829.12   167.3  828.81     187  828.48
   196.8  827.37   216.5  823.72   226.3  822.74   236.2  823.13   238.5  823.55
     246   824.9   255.8  827.12   265.7  829.57   275.5  833.34   285.4  837.99
   295.2  843.02     305  848.21   314.9  853.74   324.7  859.42   334.6     865
   354.2  875.72   364.1  880.46   383.8  889.04   393.6  893.56
#Mann= 3 , 0 , 0
       0      .1       0   216.5    .045       0   238.5      .1       0
Bank Sta=216.5,238.5
XS Rating Curve= 0 ,0
Exp/Cntr=0.3,0.1

Type RM Length L Ch R = 1 ,1891.1  ,464.8,461.2,457.4
XS GIS Cut Line= 2
     1789694.633      436108.621     1789929.008      435888.135
#Sta/Elev= 20
       0  834.89     9.8  830.81    19.5  829.05    29.2  828.44   107.3  825.18
   126.8  824.51   136.5  824.37   146.3  823.57     156  820.59  162.13  819.01
   165.8  817.92   175.5  818.04   181.3  819.35   185.3  820.26     195  823.94
   204.8  829.01   224.3  840.51   282.8  875.34     312  892.38   321.8  897.98
#Mann= 3 , 0 , 0
       0      .1       0  162.13    .045       0   181.3      .1       0
Bank Sta=162.13,181.3
XS Rating Curve= 0 ,0
Exp/Cntr=0.3,0.1

Type RM Length L Ch R = 1 ,1430    ,388.5,384.9,380.9
XS GIS Cut Line= 2
      1790071.37      436417.649     1790286.647       436131.19
#Sta/Elev= 23
       0   829.7   106.5   819.3   116.2  818.54   125.9   818.2   135.6  817.76
   145.3  815.27   154.1  812.86     155  812.61   164.6  811.89   174.3  812.42
   193.7  814.78   213.1  816.73   222.8  818.06   232.4  820.65   242.1  823.51
   251.8  826.07   261.5  828.48   271.2  831.08   280.9  834.17   290.5   837.8
   319.6  849.69     339  857.19   358.3  864.37
#Mann= 3 , 0 , 0
       0      .1       0   154.1    .045       0   174.3      .1       0
Bank Sta=154.1,174.3
XS Rating Curve= 0 ,0
Exp/Cntr=0.3,0.1

Type RM Length L Ch R = 1 ,1045.1  ,475.9,478,479.3
XS GIS Cut Line= 3
     1790463.731      436540.912     1790527.967      436415.912
     1790534.911      436315.218
#Sta/Elev= 29
       0  814.52     9.4  814.14    18.7  813.76    28.1  813.42    37.5     813
    46.8  812.57    56.2  812.25    65.6  812.08      75  811.83    84.3  810.37
    90.7  808.06    93.7  806.97   103.1  805.59   105.7  805.98   112.4  806.98
   121.8  811.02   131.2   816.4   140.5  821.18   149.7  825.53   158.9  829.89
   168.1  834.19   177.2  838.48   186.4  842.78   195.6  846.97   204.8  851.18
     214  855.37   223.1  859.55   232.3  863.66   241.5  867.71
#Mann= 3 , 0 , 0
       0      .1       0    93.7    .045       0   112.4      .1       0
Bank Sta=93.7,112.4
XS Rating Curve= 0 ,0
Exp/Cntr=0.3,0.1

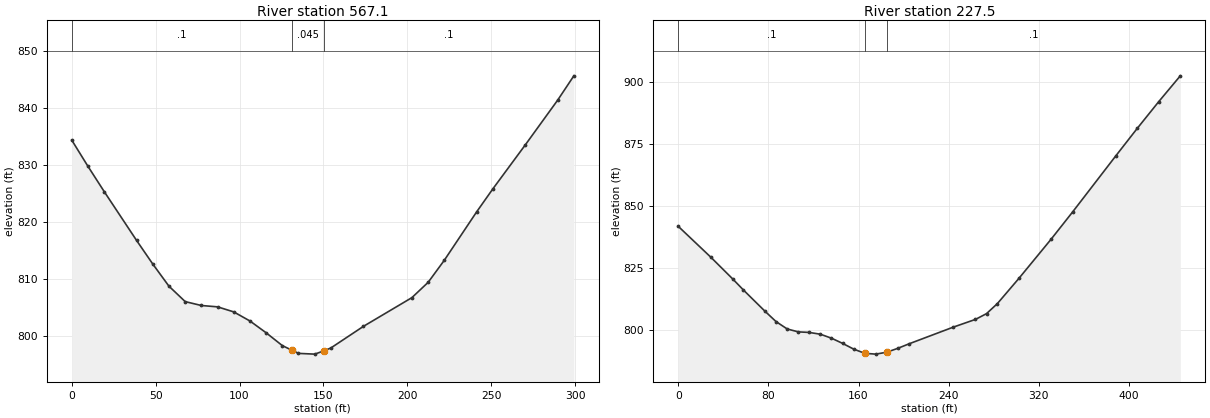
Type RM Length L Ch R = 1 ,567.1   ,336.5,339.5,342.6
XS GIS Cut Line= 2
     1790889.078      436721.468     1791045.328       436466.26
#Sta/Elev= 27
       0  834.32     9.6  829.75    19.3  825.31    38.6  816.74    48.3  812.58
    57.9  808.71    67.6     806    77.2  805.32    86.9  805.08    96.5   804.2
   106.2   802.6   115.8  800.54   125.5  798.28     131   797.5   135.1  796.92
   144.8  796.79  150.13  797.35   154.4  797.87   173.8  801.66   202.7   806.7
   212.4  809.39     222  813.25   241.3  821.75     251   825.8   270.3   833.5
   289.6  841.35   299.2   845.6
#Mann= 3 , 0 , 0
       0      .1       0     131    .045       0  150.13      .1       0
Bank Sta=131,150.13
XS Rating Curve= 0 ,0
Exp/Cntr=0.3,0.1

Type RM Length L Ch R = 1 ,227.5   ,225,227.5,230
XS GIS Cut Line= 4
     1791135.226      436863.834     1791210.247      436820.121
     1791328.622      436675.624     1791397.671      436518.066
#Sta/Elev= 30
       0   841.7    28.9  829.25    48.2  820.54    57.9  815.99    77.2  807.35
    86.8  803.27    96.7  800.29   106.5  799.12   116.3  798.89   126.2  798.17
     136  796.57   145.8  794.49   155.6  792.19   165.5  790.47   166.1  790.45
   175.3  790.14   185.1  790.91     195   792.5   204.8  794.29   244.1  801.03
   263.8  804.15   273.6  806.47   283.2   810.5   302.3  820.67     331  836.54
   350.1  847.54   388.3  870.09   407.4  881.22   426.5  892.02   445.6  902.41
#Mann= 3 , 0 , 0
       0      .1       0   166.1    .045       0   185.1      .1       0
Bank Sta=166.1,185.1
XS Rating Curve= 0 ,0
Exp/Cntr=0.3,0.1

Chan Stop Cuts=-1
Use User Specified Reach Order=0
Composite Channel Slope=5